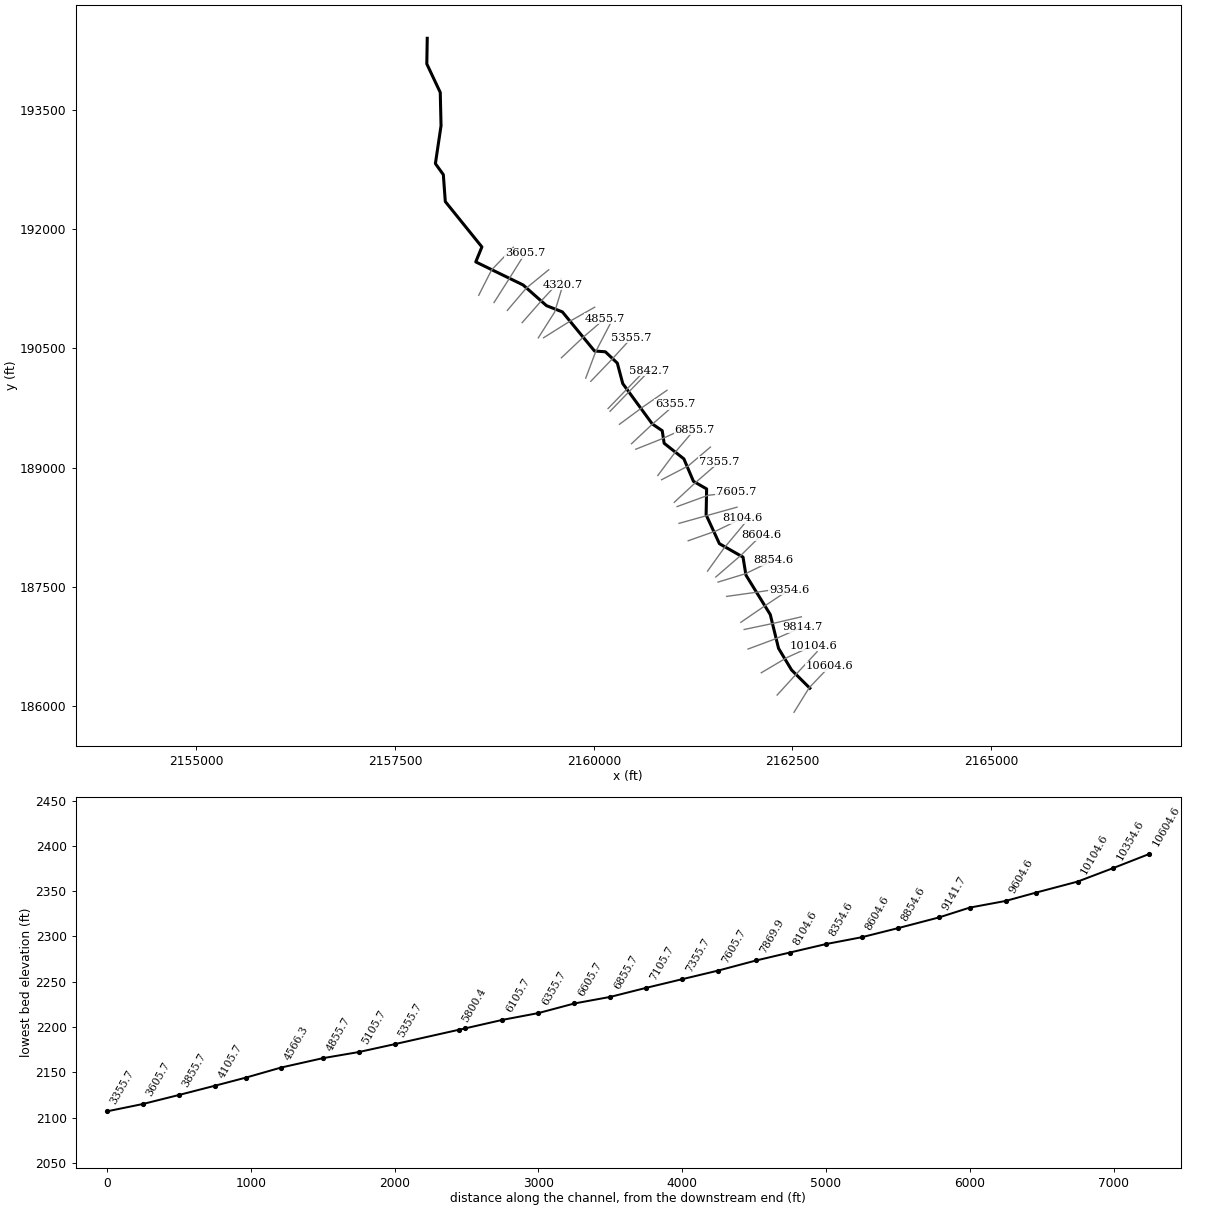
--- POTTSCKT2.prj (project) ---

Proj Title=POTTSCKT2
Current Plan=p01
Default Exp/Contr=0,0
English Units
Geom File=g01
Flow File=f01
Plan File=p01
BEGIN DESCRIPTION:
END DESCRIPTION:
DSS Export Rating Curves= 0
DSS Export Rating Curve Sorted= 0
DSS Export Volume Flow Curves= 0
DXF OffsetX= 0
DXF OffsetY= 0
DXF ScaleX= 0
DXF ScaleY= 0

--- POTTSCKT2.p01 (plan) ---

Plan Title=Floodplain
Program Version=4.00
Geom File=g01
Flow File=f01
K Sum by GR=0
Std Step Tol=0.01
Critical Tol=0.01
Num of Std Step Trials=20
Max Error Tol=0.3
Flow Tol Ratio=0.001
Split Flow NTrial=30
Split Flow Tol=0.02
Split Flow Ratio=0.02
Log Output Level=0
Friction Slope Method=1
Unsteady Friction Slope Method=2
Unsteady Bridges Friction Slope Method=1
Global Log Level=0
CheckData=False
Run HTab=0
Run UNet=0
Run PostProcess=0
UNET Theta=0
UNET Theta Warmup=0
UNET ZTol=0
UNET ZSATol=0
UNET MxIter=0
UNET MaxInSteps=0
UNET DtIC=0
UNET DtMin=0
UNET MaxCRTS=0
UNET WFStab=0
UNET SFStab=0
UNET WFX=0
UNET SFX=0
UNET DSS MLevel=0
UNET DZMax Abort=0
UNET Convert EG Bridges=0
UNET Use Existing IB Tables=0
UNET Froude Limit=0
UNET Froude Power=0
Write IC File=0
Echo Input=False
Echo Output=False
Write Detailed=0

--- POTTSCKT2.f01 (steady flow) ---

Flow Title=2010 USGS WV Regression Equation
Program Version=4.00
Number of Profiles=1
Profile Names=P100yr
River Rch & RM=POTTSCKT2,Main      ,10604.6
566.0527
River Rch & RM=POTTSCKT2,Main      ,9814.7
570.2559
River Rch & RM=POTTSCKT2,Main      ,7105.7
632.8438
River Rch & RM=POTTSCKT2,Main      ,4855.7
681.8282
River Rch & RM=POTTSCKT2,Main      ,551.9
750.9733
River Rch & RM=POTTSCKT2,Main      ,174.4
752.0545
Boundary for River Rch & Prof#=POTTSCKT2,Main      ,1
Up Type=0
Dn Type=3
Dn Slope=0.022274

--- POTTSCKT2.g01 (geometry) ---

Geom Title=LiDAR
Program Version=4.10

River Reach=POTTSCKT2       ,Main
Reach XY= 30
     2162718.765      186222.924     2162488.731      186451.873
     2162324.885      186724.226     2162220.718      187149.573
     2161914.729       187645.45     2161877.837      187872.229
     2161580.527        188041.5      2161413.43      188404.385
     2161419.937      188730.519     2161253.921      188826.005
     2161133.913       189108.34     2160885.302      189305.042
     2160860.996      189463.028     2160735.996      189548.097
     2160364.469       190055.91     2160295.892      190313.722
     2160145.718      190456.083     2160008.566        190466.5
      2159604.92       190957.82     2159404.399      191036.813
     2159110.128      191297.229     2158514.642       191587.16
     2158591.899      191775.528     2158131.437      192346.365
     2158106.656       192685.25      2158006.83      192824.139
     2158077.793      193300.701     2158068.028      193719.538
     2157898.757      194078.696     2157904.229      194401.126

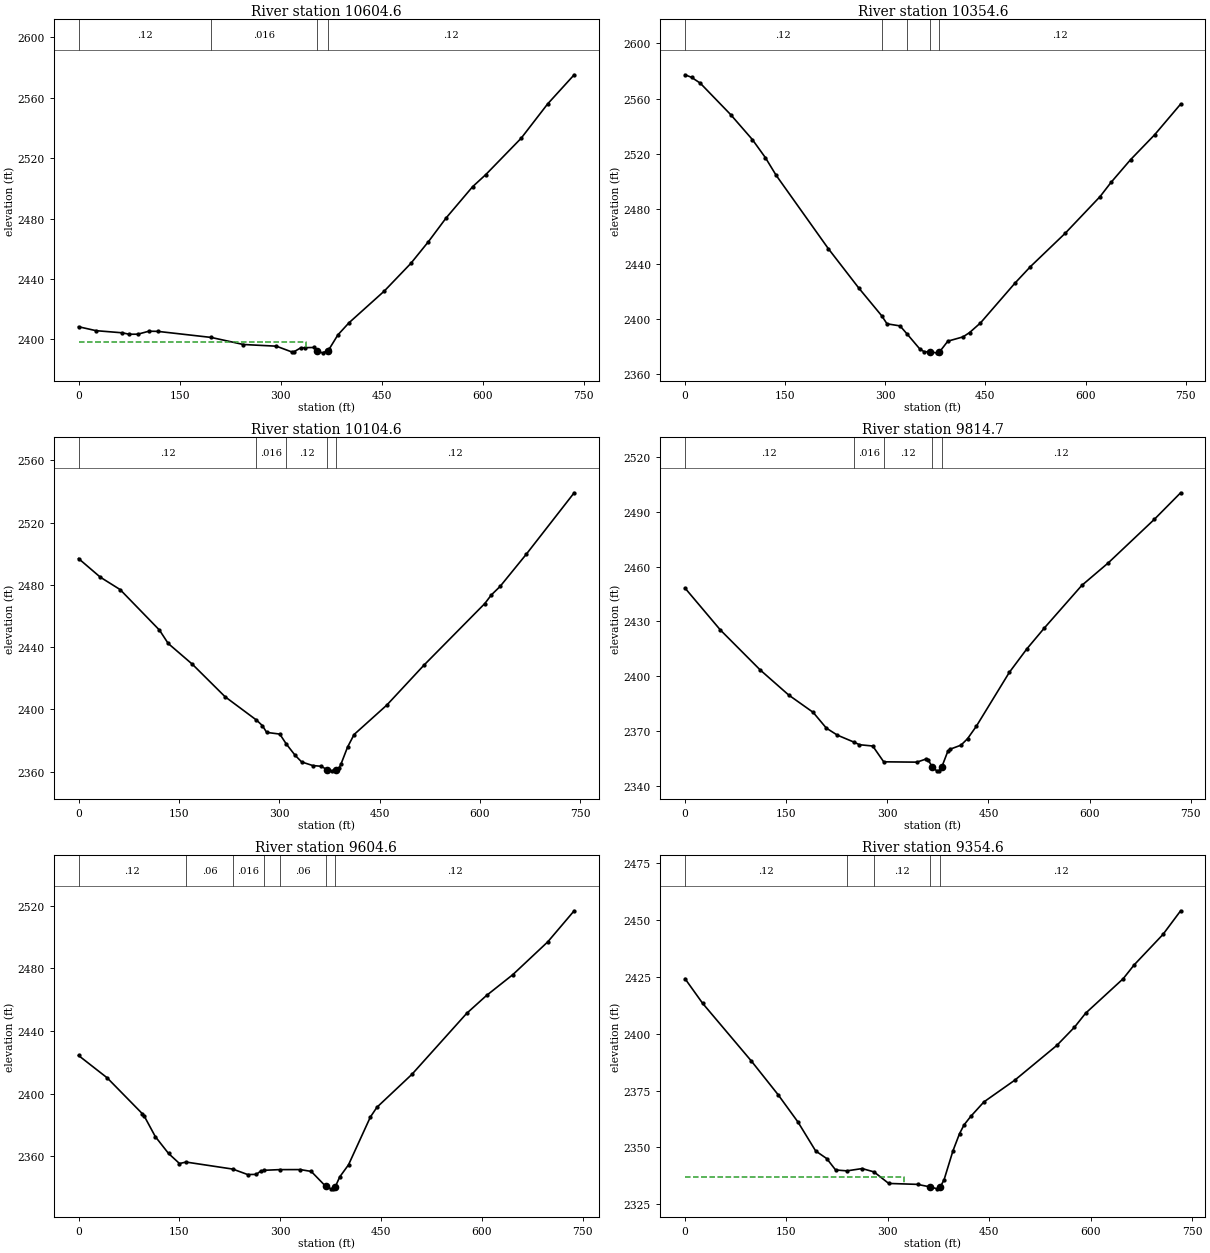
Type RM Length L Ch R = 1 ,10604.6 ,253.9,250,250.4
XS GIS Cut Line= 3
     2162519.566      185920.141     2162710.263      186228.187
     2162968.104      186498.635
#Sta/Elev= 30
       0  2408.4    26.1 2405.78    65.3 2404.36    75.1 2403.42    88.1 2403.45
   104.4 2405.42   117.5 2405.33   197.12401.302   244.8 2396.63   293.8 2395.52
   316.6 2391.72   319.9 2391.81   329.7 2394.34   336.2 2394.53   349.2 2394.66
   354.8 2392.22   362.3 2391.11   369.8 2392.46   372.1 2393.53   385.2 2403.02
   401.6 2410.99   454.1 2432.03   493.4 2450.29   519.6 2464.71   545.8 2480.38
   585.2 2501.09   604.8 2509.13   657.3 2533.19   696.6 2555.89     736 2575.19
#Mann= 4 ,-1 , 0
       0     .12       0   197.1    .016       0   354.8    .045       0
   369.8     .12       0
#XS Ineff= 2 , 0
          338.33 2398.11
Permanent Ineff=
       F       F
Bank Sta=354.8,369.8
XS Rating Curve= 0 ,0
Exp/Cntr=0.3,0.1

Type RM Length L Ch R = 1 ,10354.6 ,256.9,250,240.7
XS GIS Cut Line= 3
     2162307.223      186136.909      2162561.73      186415.582
     2162810.751      186682.456
#Sta/Elev= 30
       0 2577.23     9.8 2575.39    22.8 2571.18    68.3 2548.41   100.9 2530.28
   120.4 2517.17   136.6 2504.31   214.7 2451.14   260.3 2422.59  294.752402.402
   302.6 2396.63   322.1 2395.12  333.282388.921   351.4 2378.56   357.9 2376.48
   367.6 2376.12   377.4 2375.58  381.062376.128   393.7 2384.04   416.5 2387.16
   426.3 2390.29   442.6 2397.27   494.7 2426.37   517.5 2438.14   569.7 2462.38
   621.8 2488.94   638.1 2499.16   667.5 2515.72   703.3 2533.65   742.4 2555.97
#Mann= 5 ,-1 , 0
       0     .12       0  294.75    .016       0  333.28     .12       0
   367.6    .045       0  381.06     .12       0
Bank Sta=367.6,381.06
XS Rating Curve= 0 ,0
Exp/Cntr=0.3,0.1

Type RM Length L Ch R = 1 ,10104.6 ,293.9,289.9,289.2
XS GIS Cut Line= 3
      2162107.68      186417.122     2162434.143      186610.451
     2162763.457      186759.661
#Sta/Elev= 30
       0 2496.91    32.7 2484.89    62.2 2476.96     121 2450.94   134.1 2442.33
   170.1 2429.04   219.1 2408.13  266.092393.115   274.8  2389.6   281.3 2385.22
   300.9 2384.13  310.652377.754   323.8 2370.52   333.6 2366.23     350 2363.94
   363.1 2363.43   371.72361.151   379.4 2360.52  384.922361.152   389.2 2362.21
   392.4 2364.84   402.2 2375.76     412 2383.85   460.8 2402.71   516.2  2428.3
   607.4 2467.99   617.2 2473.53   630.2 2478.95   669.3  2499.6     741 2539.14
#Mann= 5 ,-1 , 0
       0     .12       0  266.09    .016       0  310.65     .12       0
   371.7    .045       0  384.92     .12       0
Bank Sta=371.7,384.92
XS Rating Curve= 0 ,0
Exp/Cntr=0.3,0.1

Type RM Length L Ch R = 1 ,9814.7  ,213.4,210.1,204.4
XS GIS Cut Line= 3
     2161941.145      186715.833     2162285.007      186843.575
     2162622.021      186991.514
#Sta/Elev= 30
       0 2448.27    52.4 2425.38   111.4 2403.55   153.9 2389.77     190 2380.35
   209.6 2371.72     226 2367.87  249.922364.163   258.7 2362.65   278.4 2361.93
  294.632353.305   343.9 2353.12     357 2354.78   360.3 2354.42   366.8 2350.54
   373.3 2348.37   376.6 2348.46  380.892350.591   389.6 2358.96   392.9 2360.16
   409.2  2362.4   418.9 2365.91     432 2372.74   480.8 2402.13   506.9 2415.03
   532.9 2426.46   588.3 2449.69   627.4 2461.95   695.8 2485.77   734.9 2500.33
#Mann= 5 ,-1 , 0
       0     .12       0  249.92    .016       0  294.63     .12       0
   366.8    .045       0  380.89     .12       0
Bank Sta=366.8,380.89
XS Rating Curve= 0 ,0
Exp/Cntr=0.3,0.1

Type RM Length L Ch R = 1 ,9604.6  ,240.2,250,258.1
XS GIS Cut Line= 3
     2161892.443      186961.638     2162259.988      187038.947
     2162612.256      187121.276
#Sta/Elev= 30
       0 2424.33    42.5  2410.1    94.7 2387.27      98 2385.47   114.3 2372.51
   133.9  2361.8   150.2 2355.36  160.112356.286  229.492351.807   251.5 2348.35
   264.5 2348.41   271.1 2350.57  276.042351.029  299.142351.462   329.9 2351.49
   346.2 2350.32   367.62340.874   375.6  2339.2   378.8 2339.22   382.1 2340.59
   388.6  2346.8   401.7 2354.55   434.2 2385.03     444 2391.28   496.2 2412.36
   577.6 2451.25     607 2462.61   646.1  2475.9   698.2 2496.88   737.4 2516.68
#Mann= 7 ,-1 , 0
       0     .12       0  160.11     .06       0  229.49    .016       0
  276.04     .08       0  299.14     .06       0   367.6    .045       0
   382.1     .12       0
Bank Sta=367.6,382.1
XS Rating Curve= 0 ,0
Exp/Cntr=0.3,0.1

Type RM Length L Ch R = 1 ,9354.6  ,223.7,212.8,201.9
XS GIS Cut Line= 3
      2161850.72      187052.316     2162156.248      187261.469
     2162458.195      187462.769
#Sta/Elev= 30
       0  2424.1    26.2 2413.23    98.3  2387.9   137.6 2373.22   167.1 2361.18
   193.3 2348.47   209.7 2345.12   222.8 2340.13  239.532339.727   262.1 2340.74
  279.622339.269   301.4 2334.21     344  2333.8   362.22332.705   373.5 2331.84
  377.642332.676   383.3 2335.86   396.4 2348.52   406.2 2356.11   412.8 2359.88
   422.6 2363.59   442.2 2369.99     488 2379.56   550.1  2394.8   576.2 2402.79
   592.6 2408.91   648.2 2424.06   664.5 2430.15     707 2443.47   733.2 2453.88
#Mann= 5 ,-1 , 0
       0     .12       0  239.53    .016       0  279.62     .12       0
   362.2    .045       0  377.64     .12       0
#XS Ineff= 2 , 0
           323.5 2337.19
Permanent Ineff=
       F       F
Bank Sta=362.2,377.64
XS Rating Curve= 0 ,0
Exp/Cntr=0.3,0.1

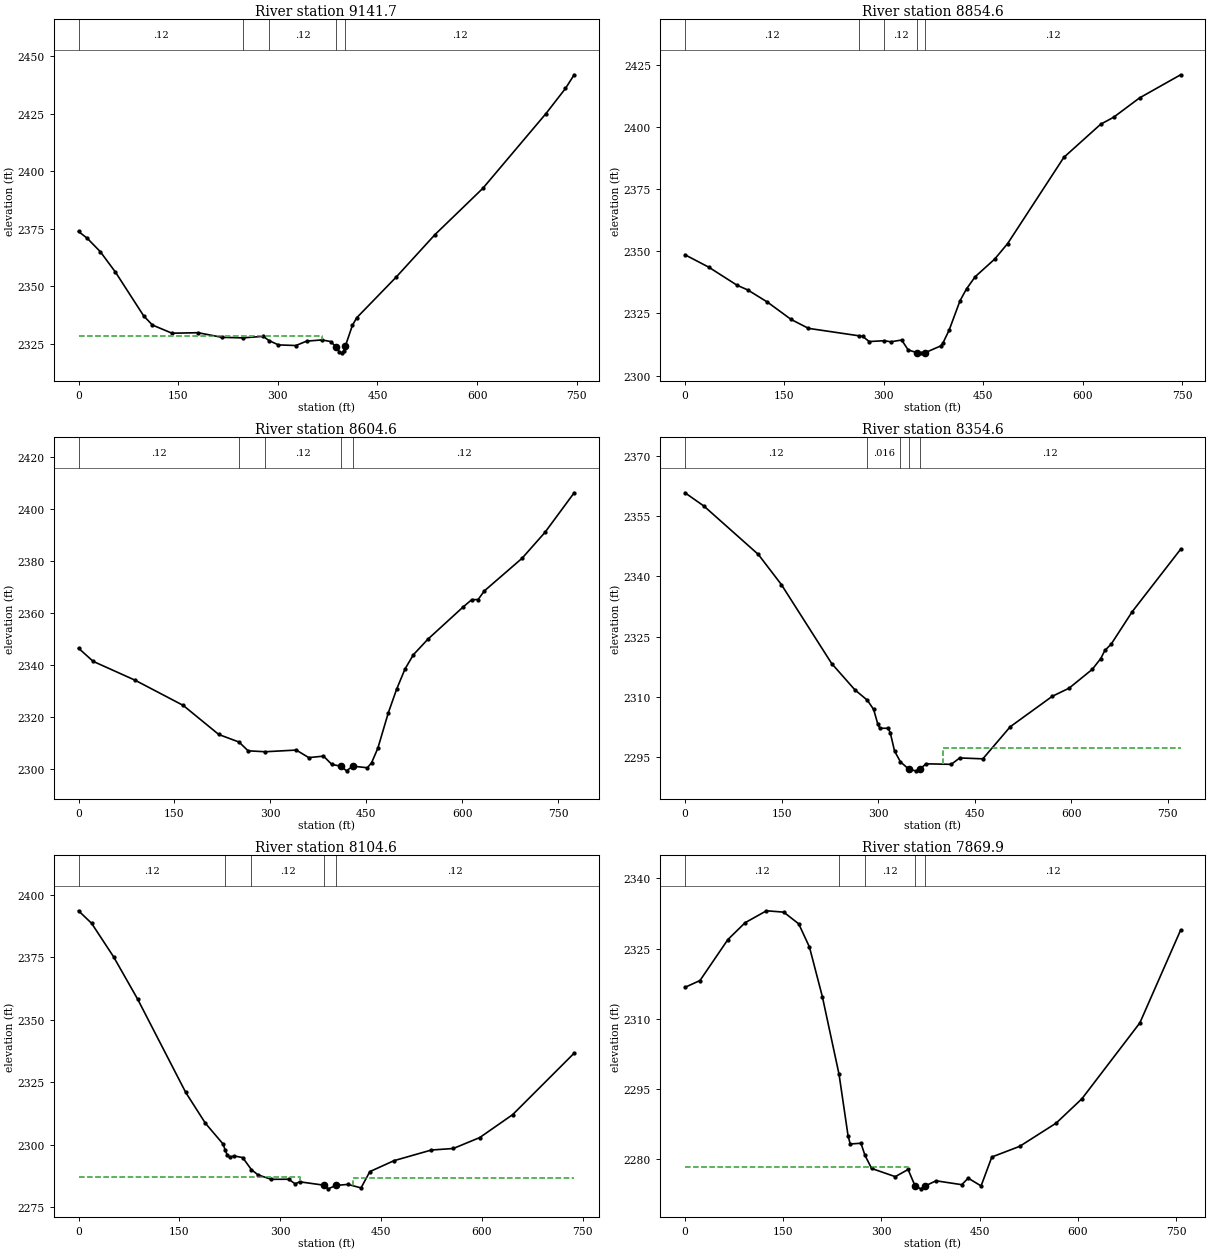
Type RM Length L Ch R = 1 ,9141.7  ,283.2,287.2,293.4
XS GIS Cut Line= 3
     2161671.864      187378.141     2162054.254      187431.379
     2162410.294      187484.929
#Sta/Elev= 30
       0 2373.81    13.1 2370.87    32.7 2365.06    55.6 2356.14    98.2 2337.07
   111.2 2333.15   140.7 2329.58     180  2329.8   215.9 2327.79  247.182327.552
   278.1 2328.22  286.852326.353     301  2324.5   327.2 2324.23   343.5 2326.15
   366.4 2326.66   379.5 2325.96  387.582323.647   392.6 2321.46   395.9 2321.05
   399.2 2321.91   401.5 2323.83   412.3 2333.02   418.8 2336.31   477.7 2353.83
   536.6 2372.46   608.6 2392.56   703.6 2425.05     733 2435.99   746.1 2441.93
#Mann= 5 ,-1 , 0
       0     .12       0  247.18    .016       0  286.85     .12       0
  387.58    .045       0   401.5     .12       0
#XS Ineff= 2 , 0
          367.08 2328.51
Permanent Ineff=
       F       F
Bank Sta=387.58,401.5
XS Rating Curve= 0 ,0
Exp/Cntr=0.3,0.1

Type RM Length L Ch R = 1 ,8854.6  ,240.1,250,257.1
XS GIS Cut Line= 3
     2161563.396      187557.971      2161907.35      187663.028
     2162257.015      187832.133
#Sta/Elev= 30
       0  2348.6      36 2343.59    78.5 2336.35    94.8 2334.43   124.2 2329.59
   160.2 2322.56   186.4 2318.98  262.972315.973   268.1  2315.8   277.9 2313.67
  300.972314.011   310.6 2313.57     327 2314.29   336.8 2310.31   349.8 2309.21
   356.4 2309.13   362.9 2309.24   385.8  2311.9     389  2312.9   398.8 2318.38
   415.1 2330.11   424.9 2334.89     438 2339.77   467.4 2346.86   486.9 2353.09
   571.8 2387.81   627.3 2401.12   646.9 2403.94     686 2411.72     748 2421.03
#Mann= 5 ,-1 , 0
       0     .12       0  262.97    .016       0  300.97     .12       0
   349.8    .045       0   362.9     .12       0
Bank Sta=349.8,362.9
XS Rating Curve= 0 ,0
Exp/Cntr=0.3,0.1

Type RM Length L Ch R = 1 ,8604.6  ,243.8,250,251.4
XS GIS Cut Line= 3
      2161535.09      187622.131     2161852.339        187896.1
     2162105.827      188146.194
#Sta/Elev= 30
       0 2346.38    22.9 2341.31    88.4 2334.07   163.7 2324.38   219.4 2313.18
  251.042310.275   265.3  2306.9  292.122306.544   340.6 2307.19   360.2 2304.28
   383.2 2304.86   396.2 2301.68   410.7 2300.95   419.2  2299.2     429 2301.01
   451.8 2300.38   458.4  2302.3   468.2 2307.89   484.5 2321.45   497.6  2330.6
   510.6 2338.32   523.7 2343.83   546.6 2349.86   602.1 2362.33   615.2 2365.05
     625 2365.07   634.8  2368.4   693.6 2380.91   729.5 2390.88   775.3 2406.15
#Mann= 5 ,-1 , 0
       0     .12       0  251.04    .016       0  292.12     .12       0
   410.7    .045       0     429     .12       0
Bank Sta=410.7,429
XS Rating Curve= 0 ,0
Exp/Cntr=0.3,0.1

Type RM Length L Ch R = 1 ,8354.6  ,263.8,250,240.4
XS GIS Cut Line= 3
     2161431.624       187696.15     2161638.121       187984.82
     2161903.881      188303.816
#Sta/Elev= 30
       0 2360.83    29.3 2357.54     114 2345.47   149.8 2337.97   227.9 2318.32
   263.8  2311.8  283.36 2309.18   293.1 2306.89   299.6 2303.24   302.8  2302.2
   315.8  2302.2   319.1 2300.99   325.6 2296.53  334.81 2293.83  347.932291.993
   358.2  2291.6   364.7 2291.97   374.5 2293.35   413.8 2293.22   426.8 2294.81
   462.8 2294.59   505.3 2302.57   570.7 2310.16   596.8 2312.18   632.8 2316.87
   645.9 2319.54   652.4 2321.58   662.2 2323.15   694.9 2331.23   770.1 2346.78
#Mann= 5 ,-1 , 0
       0     .12       0  283.36    .016       0  334.81     .12       0
  347.93    .045       0   364.7     .12       0
#XS Ineff= 2 , 0
                             401         2297.23
Permanent Ineff=
       F       F
Bank Sta=347.93,364.7
XS Rating Curve= 0 ,0
Exp/Cntr=0.3,0.1

Type RM Length L Ch R = 1 ,8104.6  ,235.9,234.6,229.8
XS GIS Cut Line= 3
      2161188.09      188078.177     2161541.176      188202.792
     2161867.445        188361.5
#Sta/Elev= 30
       0 2393.58    19.5 2388.56    52.1 2375.19    87.9 2358.24   159.5 2320.87
   188.8 2308.53   214.9 2300.28  217.992297.948   221.4 2295.75   224.7 2294.99
   231.2 2295.49   244.2 2294.81  257.192289.983     267  2287.9   286.5 2286.12
   312.6 2286.15   322.3 2284.29   328.8 2285.13   365.72283.746   371.2 2282.31
   383.12283.687   400.6 2284.08   420.2 2282.69   433.3  2289.2   469.2 2293.58
   524.8 2297.84   557.5 2298.46   596.7 2302.82   645.7    2312   737.2 2336.61
#Mann= 5 ,-1 , 0
       0     .12       0  217.99    .016       0  257.19     .12       0
   365.7    .045       0   383.1     .12       0
#XS Ineff= 2 , 0
          329.98 2287.08  408.62         2286.68
Permanent Ineff=
       F       F
Bank Sta=365.7,383.1
XS Rating Curve= 0 ,0
Exp/Cntr=0.3,0.1

Type RM Length L Ch R = 1 ,7869.9  ,261.7,264.3,260.2
XS GIS Cut Line= 2
     2161072.641      188297.183     2161801.812      188500.865
#Sta/Elev= 30
       0 2316.69    22.9 2318.15    65.6 2326.93    91.8 2330.52   124.5 2333.08
   150.8 2332.79   173.7 2330.29   190.1 2325.33   209.8 2314.72  235.372298.049
   249.1 2284.92   252.4 2283.16   268.8 2283.32  274.872280.751   285.1 2277.92
   321.2 2276.17   340.8  2277.7   351.6 2274.14   360.5 2273.56   366.6 2274.16
   383.5 2275.28   422.8 2274.45   432.6 2275.85   452.3 2274.18   468.7 2280.37
   511.3 2282.66     567 2287.63   606.3 2292.84   694.8 2309.08   757.1 2328.95
#Mann= 5 ,-1 , 0
       0     .12       0  235.37    .016       0  274.87     .12       0
   351.6    .045       0   366.6     .12       0
#XS Ineff= 2 , 0
          340.21 2278.33
Permanent Ineff=
       F       F
Bank Sta=351.6,366.6
XS Rating Curve= 0 ,0
Exp/Cntr=0.3,0.1

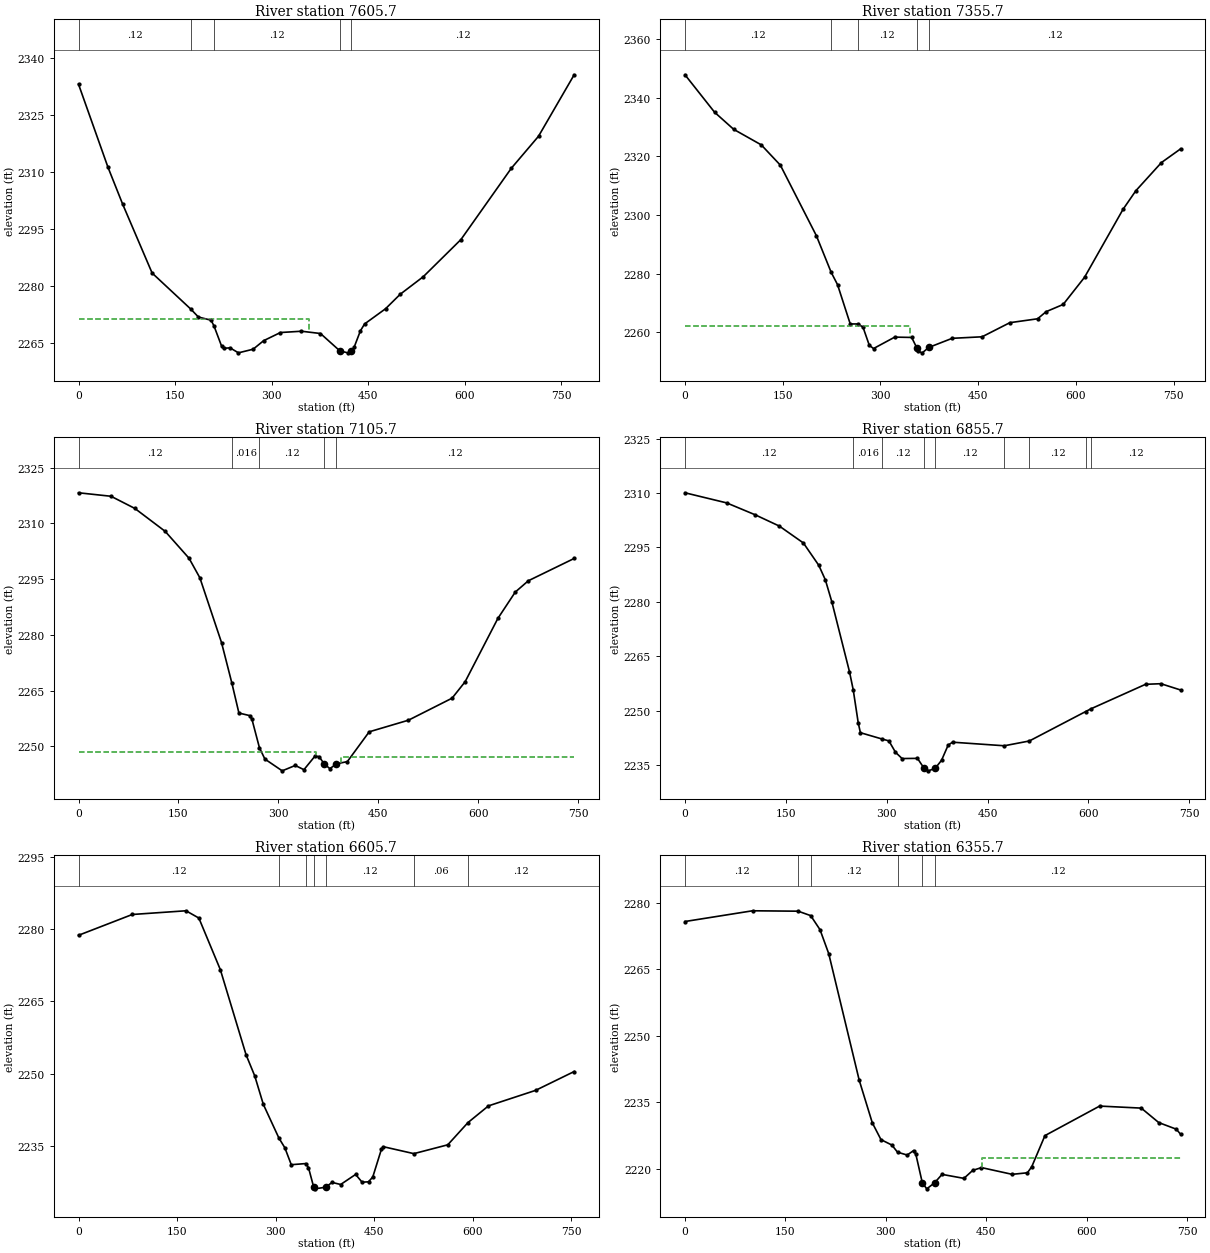
Type RM Length L Ch R = 1 ,7605.7  ,241,250,263.2
XS GIS Cut Line= 3
     2161048.336      188508.246     2161438.379       188650.54
     2161791.289      188688.692
#Sta/Elev= 30
       0    2333    45.8 2311.16    68.6 2301.47   114.4 2283.36  174.722273.849
   186.3  2271.8     206 2270.97  210.542269.452   222.3 2264.17   225.6 2263.57
   235.4 2263.71   248.5 2262.39   271.3 2263.34   287.7 2265.59   313.8 2267.73
   346.5 2268.07     376 2267.47   406.32262.876   418.4  2262.4   424.12262.821
   428.2 2263.82     438 2268.16   444.5 2269.98   477.1 2273.98   499.9 2277.79
   535.7  2282.4   594.3 2292.18   672.5  2310.9   714.8 2319.32   770.2 2335.48
#Mann= 5 ,-1 , 0
       0     .12       0  174.72    .016       0  210.54     .12       0
   406.3    .045       0   424.1     .12       0
#XS Ineff= 2 , 0
          358.31 2271.35
Permanent Ineff=
       F       F
Bank Sta=406.3,424.1
XS Rating Curve= 0 ,0
Exp/Cntr=0.3,0.1

Type RM Length L Ch R = 1 ,7355.7  ,254.6,250,250.4
XS GIS Cut Line= 3
     2161012.902      188562.502     2161277.753      188807.893
     2161579.406      189070.336
#Sta/Elev= 30
       0 2347.88    45.5 2335.07    74.8 2329.24   117.1 2323.94   146.4 2317.01
   201.7 2292.92  224.35 2280.44   234.2 2276.19   253.7 2262.77  265.192262.764
   273.2 2261.73     283 2255.45   289.5 2254.37     322 2258.27     348 2258.16
   355.82254.639   357.8 2253.42   364.3  2252.9   374.2 2254.74   410.2 2257.86
   456.1 2258.38   498.7  2263.2   541.3 2264.53   554.4 2266.96   580.6 2269.43
   613.4 2278.71   672.4 2301.89   692.1 2308.26   731.4 2317.89   760.9 2322.58
#Mann= 5 ,-1 , 0
       0     .12       0  224.35    .016       0  265.19     .12       0
   355.8    .045       0   374.2     .12       0
#XS Ineff= 2 , 0
          345.92 2262.09
Permanent Ineff=
       F       F
Bank Sta=355.8,374.2
XS Rating Curve= 0 ,0
Exp/Cntr=0.3,0.1

Type RM Length L Ch R = 1 ,7105.7  ,238.2,250,253.8
XS GIS Cut Line= 3
     2160852.719      188845.999      2161187.82      189019.642
     2161467.362      189256.913
#Sta/Elev= 30
       0 2318.26    48.8 2317.32    84.6 2314.04   130.1 2307.87   165.9 2300.63
   182.2 2295.35   214.7 2277.91  230.192267.023   240.8 2258.93     257 2258.24
   260.3  2257.3  271.592249.595   279.8 2246.53   305.8 2243.36   325.4 2244.81
   338.4 2243.67   354.6 2247.24   361.2  2247.2   368.8 2245.23   377.4 2243.95
   387.2 2245.24   403.6 2245.85   436.4 2253.87   495.3    2257   560.8 2262.93
   580.4 2267.36   629.5  2284.4   655.7 2291.52   675.3 2294.56   744.1 2300.57
#Mann= 5 ,-1 , 0
       0     .12       0  230.19    .016       0  271.59     .12       0
   368.8    .045       0   387.2     .12       0
#XS Ineff= 2 , 0
          357.15 2248.51  393.43         2247.17
Permanent Ineff=
       F       F
Bank Sta=368.8,387.2
XS Rating Curve= 0 ,0
Exp/Cntr=0.3,0.1

Type RM Length L Ch R = 1 ,6855.7  ,262.3,250,240.1
XS GIS Cut Line= 3
     2160805.644      188899.229     2161024.173      189191.979
     2161265.493      189474.902
#Sta/Elev= 30
       0 2310.05      62 2307.26   104.4 2303.98   140.3 2300.87   176.1 2296.21
     199 2290.05   208.8 2286.03   218.5 2279.93   244.6 2260.76  250.242255.712
   257.7 2246.59   260.9 2243.89  293.622242.119   303.3 2241.63   313.1 2238.49
   322.9 2236.76   345.8 2236.81   355.5 2234.11   362.1 2233.37  372.222234.085
   381.6 2236.28   391.4 2240.45   397.9 2241.27  474.972240.283  512.152241.603
  595.892249.713  603.332250.434     685 2257.23   707.8  2257.4   737.2 2255.66
#Mann= 9 ,-1 , 0
       0     .12       0  250.24    .016       0  293.62     .12       0
   355.5    .045       0  372.22     .12       0  474.97     .06       0
  512.15     .12       0  595.89     .06       0  603.33     .12       0
Bank Sta=355.5,372.22
XS Rating Curve= 0 ,0
Exp/Cntr=0.3,0.1

Type RM Length L Ch R = 1 ,6605.7  ,241.1,250,256.5
XS GIS Cut Line= 3
     2160528.561      189230.029     2160868.838       189365.43
     2161221.205      189527.548
#Sta/Elev= 30
       0 2278.73    81.8 2283.05   163.5 2283.82   183.1 2282.31   215.8 2271.59
     255  2253.9   268.1 2249.55   281.2 2243.63  304.932236.629   313.9 2234.63
   323.7 2231.11  345.832231.346   349.9 2230.49  357.892226.424   359.7  2226.1
     376 2226.44   385.8 2227.44   398.8    2227   421.6 2229.09   431.4 2227.48
   441.2 2227.56   447.7 2228.56   460.8 2234.29     464 2234.84  510.222233.406
   561.8 2235.24  592.532239.854   623.7 2243.32   695.4 2246.54   754.1 2250.45
#Mann= 7 ,-1 , 0
       0     .12       0  304.93    .016       0  345.83     .12       0
  357.89    .045       0     376     .12       0  510.22     .06       0
  592.53     .12       0
Bank Sta=357.89,376
XS Rating Curve= 0 ,0
Exp/Cntr=0.3,0.1

Type RM Length L Ch R = 1 ,6355.7  ,252.4,250,247.3
XS GIS Cut Line= 3
     2160474.392      189299.232     2160737.982      189546.112
     2161023.868      189795.355
#Sta/Elev= 30
       0 2275.79   100.9 2278.21  169.082278.117  187.782277.118   201.7 2273.95
   214.7 2268.56   260.3 2239.99   279.8 2230.41   292.8 2226.61   309.1 2225.39
  317.482223.785   331.9 2223.14   341.6 2224.15   344.9  2223.3   354.6 2216.84
   361.2 2215.52  372.912216.891     384 2218.78   416.7 2217.88   429.8 2219.68
   442.9 2220.31   488.7 2218.79   511.6 2219.14   518.1 2220.54   537.7 2227.52
   619.4 2234.18   681.6 2233.72   707.7 2230.46   733.9 2228.97   740.4 2227.82
#Mann= 6 ,-1 , 0
       0     .12       0  169.08    .016       0  187.78     .12       0
  317.48    .016       0   354.6    .045       0  372.91     .12       0
#XS Ineff= 2 , 0
                          444.17         2222.42
Permanent Ineff=
       F       F
Bank Sta=354.6,372.91
XS Rating Curve= 0 ,0
Exp/Cntr=0.3,0.1

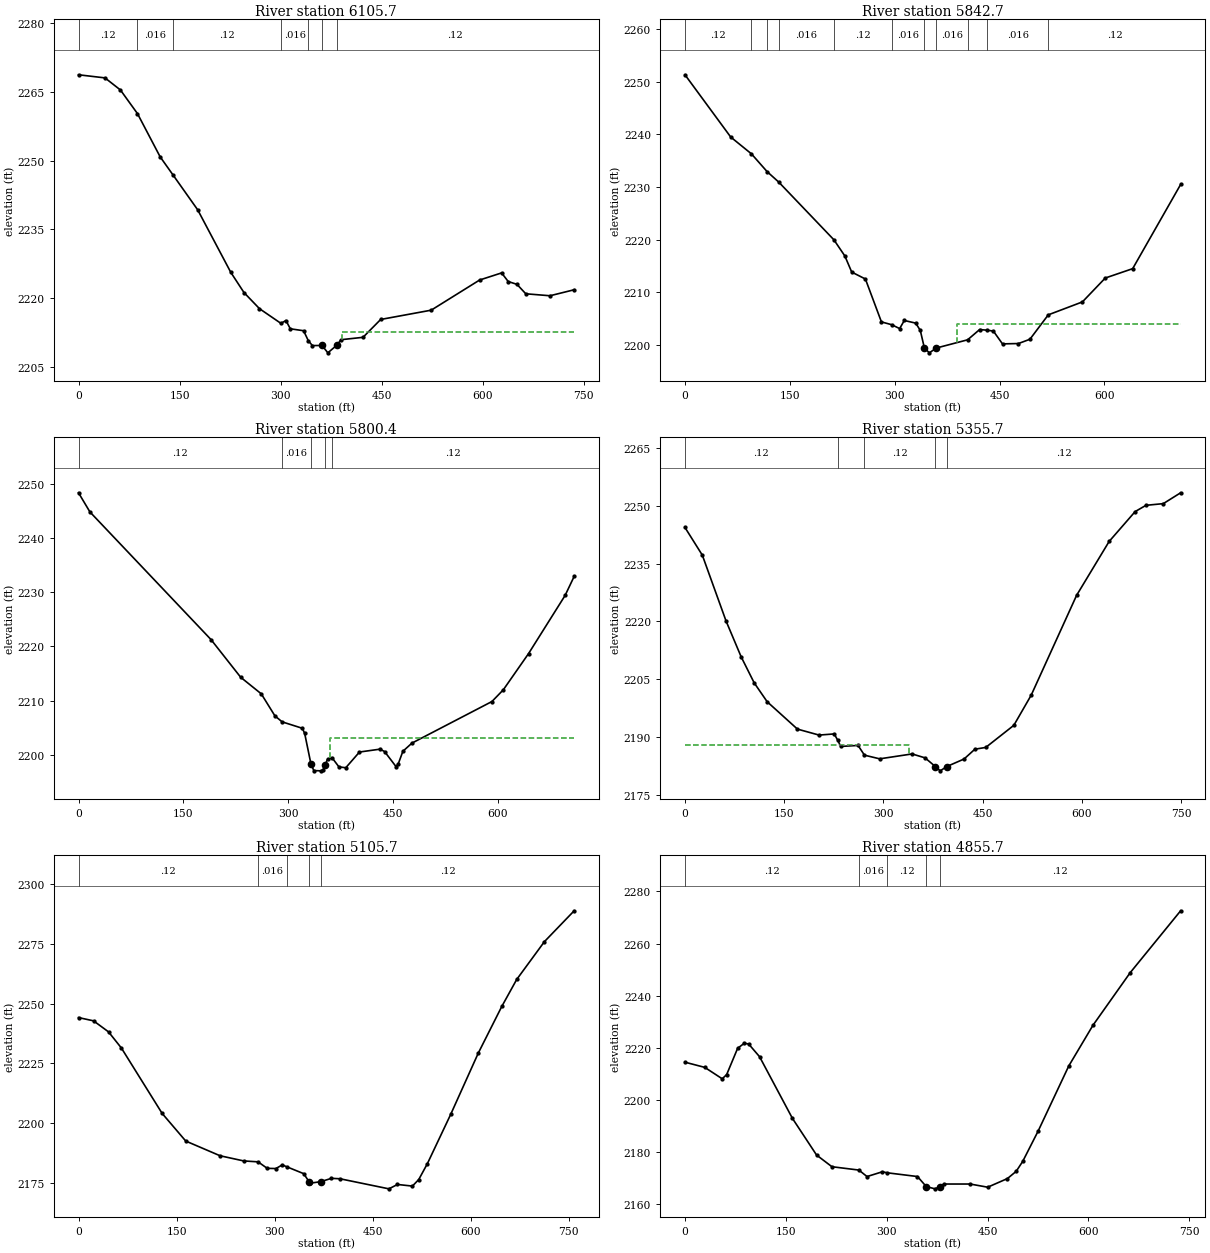
Type RM Length L Ch R = 1 ,6105.7  ,258.9,263,267.2
XS GIS Cut Line= 3
     2160322.734      189543.681     2160623.142      189765.411
      2160921.06      189971.661
#Sta/Elev= 30
       0 2268.75    39.3 2268.07    62.2 2265.43   87.532260.263   121.2 2250.82
  140.182246.886   176.9 2239.25     226  2225.6   245.6 2221.18   268.6 2217.66
  300.422214.452   307.9 2215.07   314.4 2213.26   334.1 2212.84  341.192210.628
   347.2  2209.6  361.462209.616   370.1 2208.01     3832209.629   389.7 2210.88
   422.3  2211.4   448.5  2215.3   523.5 2217.33   595.4 2223.92     628 2225.47
   637.8 2223.59   650.8 2222.97   663.9 2220.91   699.8 2220.48   735.7 2221.79
#Mann= 7 ,-1 , 0
       0     .12       0   87.53    .016       0  140.18     .12       0
  300.42    .016       0  341.19     .12       0  361.46    .045       0
     383     .12       0
#XS Ineff= 2 , 0
                          390.82         2212.59
Permanent Ineff=
       F       F
Bank Sta=361.46,383
XS Rating Curve= 0 ,0
Exp/Cntr=0.3,0.1

Type RM Length L Ch R = 1 ,5842.7  ,42.2,42.2,42.2
XS GIS Cut Line= 2
      2160204.45      189707.129     2160697.939      190216.243
#Sta/Elev= 30
       0 2251.34    65.4 2239.51   95.032236.315  117.472232.935     134 2230.96
  213.032219.974   228.7  2216.9   238.5 2213.84   258.1 2212.52     281 2204.37
  295.63 2203.84   307.1  2203.1   313.7 2204.64     330 2204.14   336.6 2202.76
  342.452199.406   349.6 2198.49   359.4  2199.4  404.282200.966   421.5 2202.92
  432.092202.791   441.1 2202.63   454.2 2200.19     477 2200.26   493.4 2201.07
  519.682205.712   568.5 2208.17   601.2 2212.71   640.4 2214.49     709 2230.49
#Mann= 11 ,-1 , 0
       0     .12       0   95.03    .016       0  117.47     .12       0
     134    .016       0  213.03     .12       0  295.63    .016       0
  342.45    .045       0   359.4    .016       0  404.28     .12       0
  432.09    .016       0  519.68     .12       0
#XS Ineff= 2 , 0
                          389.05          2203.9
Permanent Ineff=
       F       F
Bank Sta=342.45,359.4
XS Rating Curve= 0 ,0
Exp/Cntr=0.3,0.1

Type RM Length L Ch R = 1 ,5800.4  ,444.3,444.8,445.2
XS GIS Cut Line= 2
      2160179.71      189742.285       2160673.2        190251.4
#Sta/Elev= 30
       0 2248.33    16.3  2244.8   189.5 2221.25     232 2214.29   261.4 2211.24
     281 2207.16  291.272206.066   320.2 2204.88   323.5 2203.94  332.522198.273
   336.6 2197.08   346.4 2197.03   349.6 2197.14   352.9 2198.19   356.2 2199.16
   362.62199.462   372.5 2197.76   382.3  2197.6   401.9  2200.5   431.3 2201.03
   437.8 2200.59   454.2 2197.81   457.4 2198.32     464 2200.64     477 2202.15
   591.4 2209.82   607.7 2211.99   643.7 2218.65     696 2229.38     709  2232.9
#Mann= 5 ,-1 , 0
       0     .12       0  291.27    .016       0  332.52    .045       0
   352.9    .016       0   362.6     .12       0
#XS Ineff= 2 , 0
                          359.35         2203.12
Permanent Ineff=
       F       F
Bank Sta=332.52,352.9
XS Rating Curve= 0 ,0
Exp/Cntr=0.3,0.1

Type RM Length L Ch R = 1 ,5355.7  ,240.1,250,255.4
XS GIS Cut Line= 3
     2159962.299      190084.704     2160229.704      190362.835
     2160474.583      190631.231
#Sta/Elev= 30
       0 2244.41    26.2 2237.23    62.1 2220.11      85 2210.78   104.6 2204.05
   124.2 2199.15     170 2192.03   202.7 2190.48   225.6 2190.78  230.972189.112
   235.4 2187.53   261.6 2187.79  271.29 2185.26   294.3 2184.31   343.3 2185.58
   362.9 2184.56   378.52182.296   385.8 2181.19   395.82182.312   421.8 2184.26
   438.2 2186.81   454.6 2187.27   497.1 2193.02   523.3 2200.84     592  2226.8
   641.1 2240.78   680.4 2248.54   696.8 2250.17     723 2250.61   749.2 2253.43
#Mann= 5 ,-1 , 0
       0     .12       0  230.97    .016       0  271.29     .12       0
   378.5    .045       0   395.8     .12       0
#XS Ineff= 2 , 0
          338.28 2187.89
Permanent Ineff=
       F       F
Bank Sta=378.5,395.8
XS Rating Curve= 0 ,0
Exp/Cntr=0.3,0.1

Type RM Length L Ch R = 1 ,5105.7  ,259.3,250,241.3
XS GIS Cut Line= 3
     2159898.648      190124.628      2160024.58      190459.221
     2160209.686       190814.43
#Sta/Elev= 30
       0 2244.16      23 2242.79    45.9 2238.18    65.6 2231.41   127.9 2204.05
     164 2192.49   216.5 2186.33   252.6 2184.17  274.612183.782   288.6 2181.07
   301.8 2180.98   311.6 2182.51  318.522181.717   344.4 2178.84  352.592175.464
   354.2 2174.84   370.5  2175.5   386.8 2176.88   399.8 2176.71   474.7 2172.49
   487.8 2174.32   510.6 2173.64   520.3 2176.38   533.4 2182.96   569.2 2203.66
   611.5 2229.37   647.3 2248.81   670.1  2260.1   712.5 2275.93     758 2288.85
#Mann= 5 ,-1 , 0
       0     .12       0  274.61    .016       0  318.52     .12       0
  352.59    .045       0   370.5     .12       0
Bank Sta=352.59,370.5
XS Rating Curve= 0 ,0
Exp/Cntr=0.3,0.1

Type RM Length L Ch R = 1 ,4855.7  ,293.7,289.4,285.2
XS GIS Cut Line= 3
     2159592.555      190380.612     2159860.323      190633.833
      2160139.77      190874.062
#Sta/Elev= 30
       0 2214.39    29.4  2212.4    55.4 2208.01      62 2209.64    78.3 2219.73
    88.1 2221.65    94.6  2221.4   110.9  2216.5   159.8 2192.79   195.7  2178.7
   218.5 2174.22  258.542172.935   270.7 2170.44   293.5 2172.28  300.452171.895
   345.7 2170.45   358.8 2166.59   371.8 2165.72   378.82166.518   384.8 2167.57
     424 2167.57   450.1 2166.35   479.4 2169.66   492.5 2172.45   502.2 2176.27
   525.1 2187.91   570.7 2212.96   606.6 2228.56     662 2248.79     737 2272.58
#Mann= 5 ,-1 , 0
       0     .12       0  258.54    .016       0  300.45     .12       0
   358.8    .045       0   378.8     .12       0
Bank Sta=358.8,378.8
XS Rating Curve= 0 ,0
Exp/Cntr=0.3,0.1

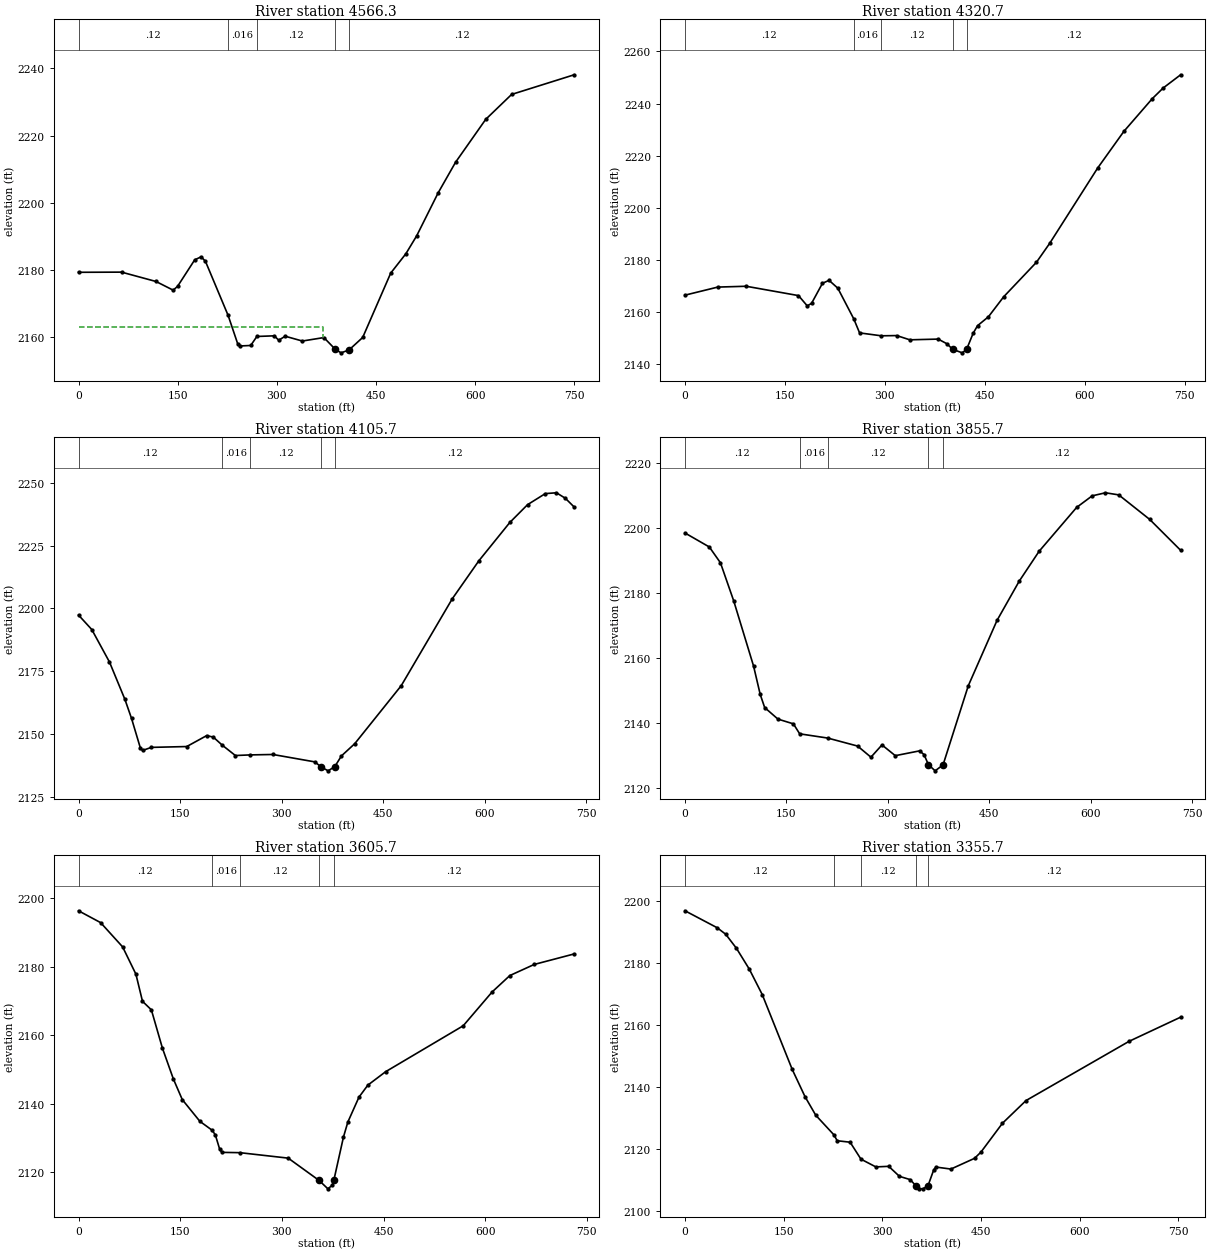
Type RM Length L Ch R = 1 ,4566.3  ,228.7,245.6,262.7
XS GIS Cut Line= 3
     2159368.061      190632.697     2159693.461      190836.929
     2160011.543      191017.298
#Sta/Elev= 30
       0 2179.36    65.1 2179.41   117.2 2176.63   143.2 2174.05   149.8 2175.17
   175.8 2183.07   185.6 2183.97   192.1 2182.59  226.352166.532   240.9 2158.06
   244.2 2157.46   260.5 2157.61  269.822160.286   296.3 2160.48   302.8 2159.16
   312.6 2160.36   338.6 2158.93   371.2 2159.96   388.52156.453   397.2 2155.42
   409.22156.273   429.9 2159.99   472.3 2179.12   495.2 2184.87   511.5 2190.18
   544.2 2203.03   570.3 2212.04     616 2224.82   655.2 2232.23   749.8 2238.07
#Mann= 5 ,-1 , 0
       0     .12       0  226.35    .016       0  269.82     .12       0
   388.5    .045       0   409.2     .12       0
#XS Ineff= 2 , 0
          370.53 2163.03
Permanent Ineff=
       F       F
Bank Sta=388.5,409.2
XS Rating Curve= 0 ,0
Exp/Cntr=0.3,0.1

Type RM Length L Ch R = 1 ,4320.7  ,224.7,215,204.5
XS GIS Cut Line= 3
     2159301.767      190631.533     2159507.194       190955.21
     2159612.335      191300.146
#Sta/Elev= 30
       0 2166.43    49.2 2169.53    91.8 2169.85   170.4 2166.26   183.5 2162.33
     190 2163.28   206.4    2171   216.3 2172.12   229.4 2169.11   253.32157.362
   262.1 2151.94  294.682150.822   317.8 2150.91   337.5 2149.28   380.1 2149.56
   393.2 2147.76  401.752145.641   416.2 2144.28   422.7  2145.6   432.5 2151.75
   439.1  2154.7   455.5 2158.13   478.4 2165.81   527.6 2179.07   547.3 2186.27
   619.4 2215.23   658.7 2229.29   701.4 2241.88   717.7 2245.96     744 2251.06
#Mann= 5 ,-1 , 0
       0     .12       0   253.3    .016       0  294.68     .12       0
  401.75    .045       0   422.7     .12       0
Bank Sta=401.75,422.7
XS Rating Curve= 0 ,0
Exp/Cntr=0.3,0.1

Type RM Length L Ch R = 1 ,4105.7  ,249.6,250,246.9
XS GIS Cut Line= 3
     2159098.693      190823.224      2159342.17       191099.91
     2159589.047      191366.303
#Sta/Elev= 30
       0 2197.35    19.6 2191.59    45.7 2178.67    68.5 2163.79    78.3 2156.19
    91.3 2144.46    94.6 2143.46   107.6 2144.68   159.8 2145.01   189.2 2149.36
     199 2148.77  212.322145.538   231.6 2141.44  253.422141.681     287 2141.85
     349  2138.9     3582136.923   368.6 2135.34   378.4 2137.04   388.2 2141.28
   407.8 2146.14   476.5 2169.25   551.8 2203.82   591.1 2218.96   636.9 2234.24
     663  2241.3   689.2  2245.7   705.6 2246.03   718.7 2243.86   731.8 2240.36
#Mann= 5 ,-1 , 0
       0     .12       0  212.32    .016       0  253.42     .12       0
     358    .045       0   378.4     .12       0
Bank Sta=358,378.4
XS Rating Curve= 0 ,0
Exp/Cntr=0.3,0.1

Type RM Length L Ch R = 1 ,3855.7  ,246.7,250,257.2
XS GIS Cut Line= 3
      2158912.11      190976.952     2159151.921      191258.398
     2159432.855      191488.253
#Sta/Elev= 30
       0  2198.5      36 2194.18    52.4 2189.32      72 2177.59   101.4 2157.45
   111.2 2148.72   117.8 2144.66   137.4  2141.1   160.3 2139.63  169.562136.555
  211.122135.244   255.2 2132.78   274.9 2129.35   291.2 2133.13   310.9 2129.82
   346.8  2131.3   353.4 2130.15   359.9 2127.04   369.8 2125.14   381.52126.979
   418.8 2151.38   461.3 2171.54     494 2183.61   523.4 2192.83     579 2206.39
   601.9 2209.95   621.6  2210.9   641.2 2210.25     687 2202.68   732.7 2193.16
#Mann= 5 ,-1 , 0
       0     .12       0  169.56    .016       0  211.12     .12       0
   359.9    .045       0   381.5     .12       0
Bank Sta=359.9,381.5
XS Rating Curve= 0 ,0
Exp/Cntr=0.3,0.1

Type RM Length L Ch R = 1 ,3605.7  ,247.5,250,244.8
XS GIS Cut Line= 3
     2158744.648      191075.978     2158942.208      191386.446
     2159134.756      191694.518
#Sta/Elev= 30
       0 2196.26    32.6 2192.81    65.1 2185.73    84.7 2177.78    94.4 2169.87
   107.5 2167.38   123.8 2156.22     140 2147.21   153.1 2141.22   179.1 2134.88
  197.192132.285   201.9 2130.92   208.4 2126.68   211.7 2125.84  238.032125.753
   309.4 2124.16     355 2117.65     368 2115.21   374.5  2116.3  376.652117.655
   390.9  2130.3   397.4 2134.69   413.8 2141.94   426.9 2145.44   453.1 2149.35
   567.6 2162.74   610.2 2172.59   636.4 2177.38   672.4 2180.62   731.3 2183.68
#Mann= 5 ,-1 , 0
       0     .12       0  197.19    .016       0  238.03     .12       0
     355    .045       0  376.65     .12       0
Bank Sta=355,376.65
XS Rating Curve= 0 ,0
Exp/Cntr=0.3,0.1

Type RM Length L Ch R = 1 ,3355.7  ,261.2,241.7,228.6
XS GIS Cut Line= 3
     2158551.939      191167.008     2158714.317      191486.688
     2158987.553       191771.73
#Sta/Elev= 30
       0 2196.83    48.9 2191.36    61.9 2189.26    78.2 2184.73    97.8 2177.99
   117.4 2169.81     163 2145.64   182.5 2136.83   198.8 2130.85  226.442124.512
   231.4 2122.62     251 2122.15   267.52116.676   290.1 2114.18   309.7 2114.36
     326 2111.13   342.3 2110.08  350.622108.177   355.3  2107.2   361.8  2107.1
   369.52108.164   378.1 2113.23   381.4 2114.13   404.2 2113.48   440.1 2116.94
   449.9 2118.96   482.6 2128.27   518.4 2135.59   675.1 2154.71   753.4  2162.5
#Mann= 5 ,-1 , 0
       0     .12       0  226.44    .016       0   267.5     .12       0
  350.62    .045       0   369.5     .12       0
Bank Sta=350.62,369.5
XS Rating Curve= 0 ,0
Exp/Cntr=0.3,0.1