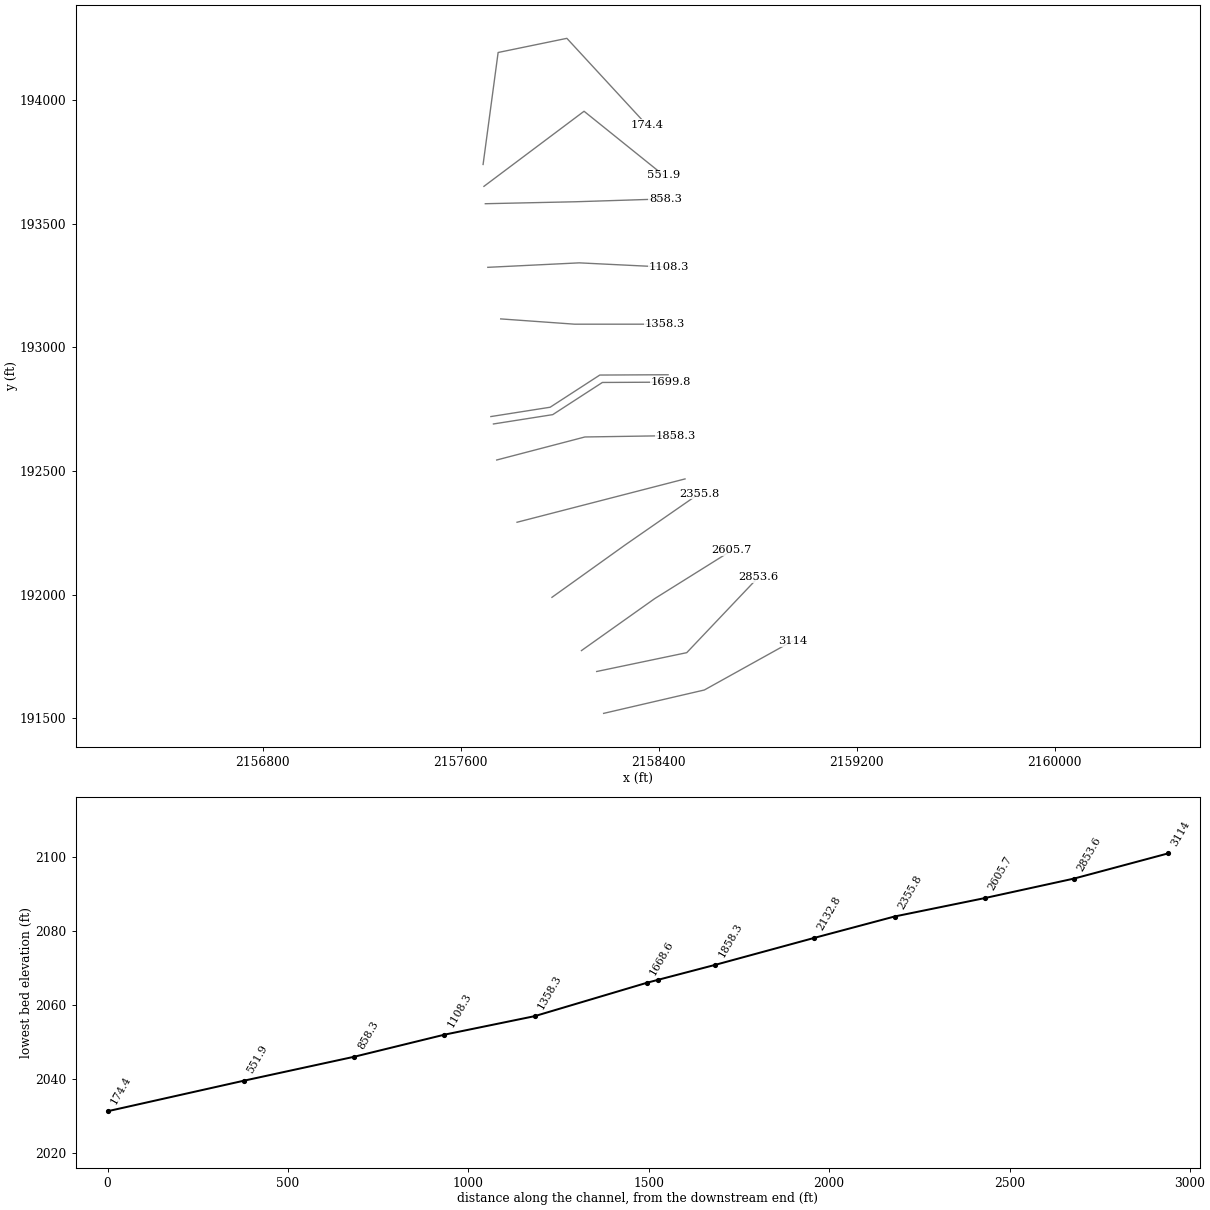
HEC-RAS study POTTSCKT2.prj: POTTSCKT2

--- POTTSCKT2.g01 (geometry) --- (continued)

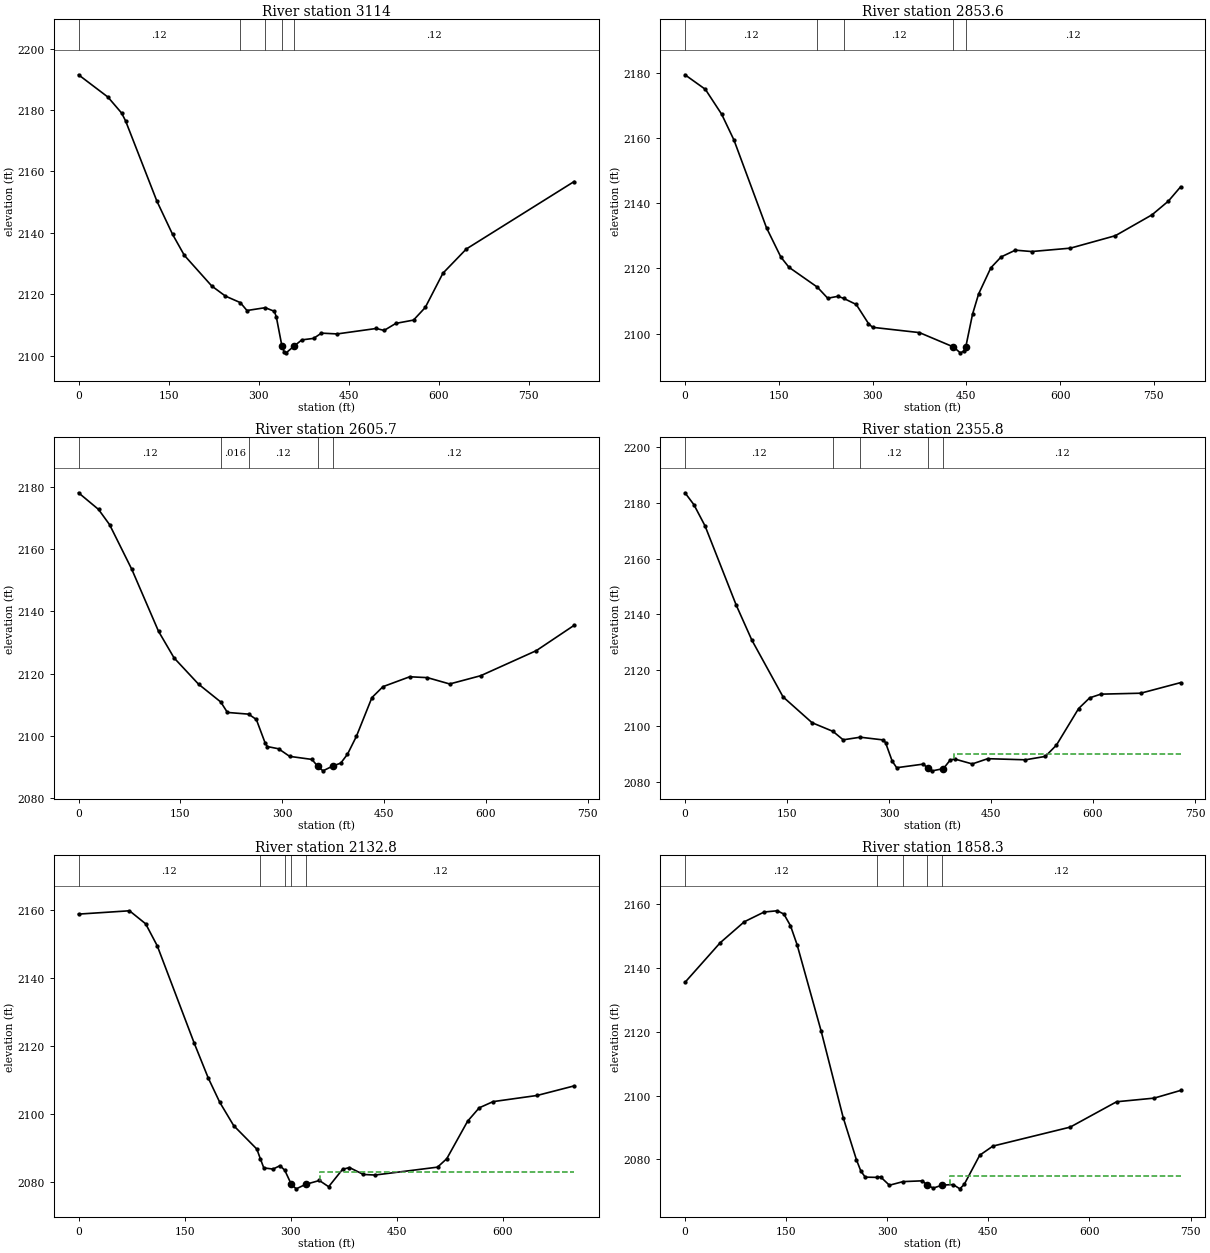
Type RM Length L Ch R = 1 ,3114    ,247.6,260.4,272.7
XS GIS Cut Line= 3
     2158177.036      191518.994     2158584.023      191613.625
     2158940.595      191811.972
#Sta/Elev= 30
       0  2191.5      49 2184.24    71.8 2179.03    78.4  2176.5   130.6 2150.33
   156.7 2139.52   176.3 2132.68     222 2122.68   244.8 2119.39  269.532117.273
   280.7 2114.69  311.182115.612   326.4 2114.42   329.7 2112.52  339.022103.024
   342.8 2101.15     346  2100.9   359.1 2103.08   372.1 2105.12   391.7 2105.61
   404.8 2107.32   430.9 2107.06   496.2 2108.84   509.2  2108.2   528.8  2110.5
   558.2 2111.57   577.8 2115.69   607.2 2126.84   646.3 2134.75   825.9 2156.72
#Mann= 5 ,-1 , 0
       0     .12       0  269.53    .016       0  311.18     .12       0
  339.02    .045       0   359.1     .12       0
Bank Sta=339.02,359.1
XS Rating Curve= 0 ,0
Exp/Cntr=0.3,0.1

Type RM Length L Ch R = 1 ,2853.6  ,252.1,247.9,242.1
XS GIS Cut Line= 3
     2158148.988       191688.46     2158512.843      191764.667
     2158802.422      192070.208
#Sta/Elev= 30
       0 2179.31    32.6 2174.85    58.7 2167.21    78.3 2159.33   130.4 2132.42
   153.3 2123.47   166.3 2120.33   211.7 2114.24   228.3 2110.84   244.6 2111.43
  253.632110.814   273.9 2108.93   293.5 2103.07     300 2101.93     375 2100.31
   429.42095.913   440.3 2094.11   446.8  2094.7  449.062095.899   459.9 2105.96
   469.6 2112.15   489.2 2120.17   505.6  2123.5   528.4 2125.57   554.5 2125.15
   616.5 2126.19   688.3    2130     747 2136.41   773.1  2140.6   792.7 2144.99
#Mann= 5 ,-1 , 0
       0     .12       0   211.7    .016       0  253.63     .12       0
   429.4    .045       0  449.06     .12       0
Bank Sta=429.4,449.06
XS Rating Curve= 0 ,0
Exp/Cntr=0.3,0.1

Type RM Length L Ch R = 1 ,2605.7  ,249.6,249.9,250.7
XS GIS Cut Line= 3
     2158087.426      191773.104     2158383.759      191983.654
      2158694.58      192178.303
#Sta/Elev= 30
       0 2178.01    29.5 2172.67    45.8 2167.78    78.6 2153.42   117.9 2133.58
   140.8 2125.05   176.8 2116.64  209.522110.923   219.4 2107.56   250.62107.014
     262 2105.31   275.1 2097.69   278.4 2096.61   294.7 2095.91   311.1 2093.47
   343.9 2092.49   352.22090.359   360.2 2088.83   374.8 2090.39   386.4 2091.31
   396.3 2094.16   409.4 2099.87   432.3 2112.32   448.6 2115.83     488    2119
   514.1 2118.72   546.9 2116.69   592.7 2119.35   674.6 2127.39   730.3 2135.51
#Mann= 5 ,-1 , 0
       0     .12       0  209.52    .016       0   250.6     .12       0
   352.2    .045       0   374.8     .12       0
Bank Sta=352.2,374.8
XS Rating Curve= 0 ,0
Exp/Cntr=0.3,0.1

Type RM Length L Ch R = 1 ,2355.8  ,230.9,223,214.4
XS GIS Cut Line= 3
     2157968.218      191988.653     2158263.837      192200.491
     2158563.717      192408.764
#Sta/Elev= 30
       0 2183.65    13.1 2179.39    29.5 2171.76    75.4  2143.3    98.3 2130.79
   144.2  2110.4   186.8 2101.14  217.682098.014   232.6 2094.99  257.652095.929
   291.6 2094.95   294.9 2093.98   304.7 2087.34   311.3 2084.98   350.6 2086.28
   357.1 2084.72   363.7 2083.86     380 2084.66   389.8 2087.68   396.3 2088.12
   422.4 2086.34   445.2 2088.22   500.6 2087.82   529.9 2089.04   546.2  2093.1
   578.8 2106.22   595.1 2110.06   611.4 2111.38   670.1 2111.72   728.8 2115.52
#Mann= 5 ,-1 , 0
       0     .12       0  217.68    .016       0  257.65     .12       0
   357.1    .045       0     380     .12       0
#XS Ineff= 2 , 0
                          395.26          2089.8
Permanent Ineff=
       F       F
Bank Sta=357.1,380
XS Rating Curve= 0 ,0
Exp/Cntr=0.3,0.1

Type RM Length L Ch R = 1 ,2132.8  ,274.4,274.5,268.9
XS GIS Cut Line= 2
     2157827.079      192292.445     2158505.898      192467.792
#Sta/Elev= 30
       0 2158.74    72.1 2159.72      95 2155.89   111.4 2149.42   163.8 2120.78
   183.5 2110.62   199.8 2103.48   219.5 2096.63   252.3 2089.73  257.15 2086.92
   262.1 2084.22   275.2 2083.87     285 2084.88  291.772083.515  301.082079.367
     308 2078.07   321.1 2079.37   340.7 2080.52   353.8 2078.69   373.5  2083.8
   383.3 2084.32     403 2082.29   419.4 2082.12   507.8 2084.44   520.9 2086.92
   550.4 2097.94   566.8 2101.86   586.4 2103.68   648.7 2105.49   701.1  2108.3
#Mann= 5 ,-1 , 0
       0     .12       0  257.15    .016       0  291.77     .12       0
  301.08    .045       0   321.1     .12       0
#XS Ineff= 2 , 0
                          341.36         2083.01
Permanent Ineff=
       F       F
Bank Sta=301.08,321.1
XS Rating Curve= 0 ,0
Exp/Cntr=0.3,0.1

Type RM Length L Ch R = 1 ,1858.3  ,150.6,158.5,171.2
XS GIS Cut Line= 3
     2157744.956      192544.352     2158101.339       192637.56
     2158468.103       192643.14
#Sta/Elev= 30
       0 2135.45    52.2 2147.85      88 2154.43   117.4 2157.48   136.9 2157.87
   146.7 2156.84   156.5 2153.19   166.3 2147.24   202.1  2120.1   234.7 2093.09
   254.3 2079.91   260.8  2076.4   267.3 2074.45  284.962074.375   290.1 2074.54
   303.2 2071.92  323.482073.052   352.1  2073.3  359.272071.939   368.4 2071.03
   381.5 2071.96   397.8 2072.13   407.7 2070.79   414.2 2072.18   437.2 2081.32
   456.8 2084.18   571.4 2090.12   640.2 2098.06   695.9  2099.2   735.2 2101.61
#Mann= 5 ,-1 , 0
       0     .12       0  284.96    .016       0  323.48     .12       0
  359.27    .045       0   381.5     .12       0
#XS Ineff= 2 , 0
                          393.67         2074.69
Permanent Ineff=
       F       F
Bank Sta=359.27,381.5
XS Rating Curve= 0 ,0
Exp/Cntr=0.3,0.1

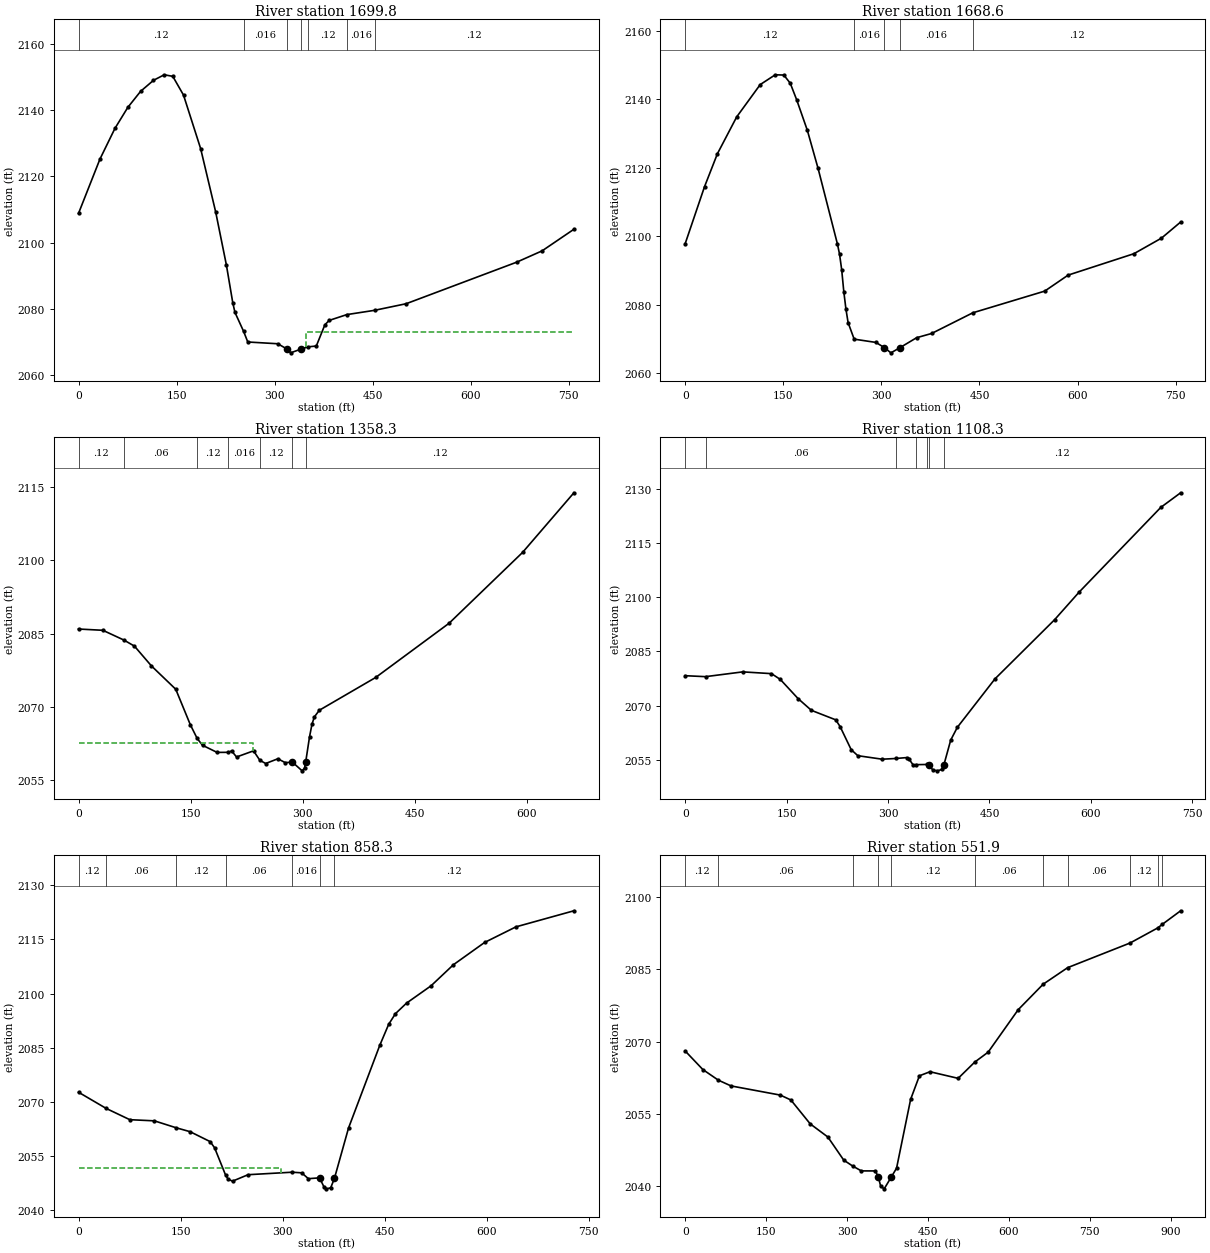
Type RM Length L Ch R = 1 ,1699.8  ,31.1,31.2,31.1
XS GIS Cut Line= 4
     2157731.793      192690.202     2157971.377      192727.962
     2158171.898       192858.17     2158447.939      192859.472
#Sta/Elev= 30
       0 2108.79    32.8 2125.18    55.7 2134.43    75.4 2140.77      95 2145.62
   114.7 2148.94   131.1 2150.61   144.2 2150.14   160.6 2144.49   186.8 2128.35
   209.8 2109.24   226.2 2093.24     236  2081.8   239.3 2078.94  252.422073.267
   258.9 2070.02   304.8 2069.49  319.082067.874   324.4 2066.75   340.62067.902
  351.42 2068.57   363.7  2068.8   376.8  2075.2   383.4 2076.53  410.432078.284
  452.792079.573   501.1 2081.56     670 2094.08     709  2097.5   757.7 2104.02
#Mann= 7 ,-1 , 0
       0     .12       0  252.42    .016       0  319.08    .045       0
   340.6    .016       0  351.42     .12       0  410.43    .016       0
  452.79     .12       0
#XS Ineff= 2 , 0
                           348.4         2073.18
Permanent Ineff=
       F       F
Bank Sta=319.08,340.6
XS Rating Curve= 0 ,0
Exp/Cntr=0.3,0.1

Type RM Length L Ch R = 1 ,1668.6  ,324.9,310.3,297
XS GIS Cut Line= 4
     2157721.377       192720.15      2157960.96       192757.91
     2158161.481      192888.118     2158437.523       192889.42
#Sta/Elev= 30
       0 2097.86    29.5 2114.44    49.2 2124.06    78.7 2134.82   114.7 2144.26
   137.7 2147.12   150.8 2147.04   160.6 2144.66   170.4 2139.84   186.8 2130.88
   203.2 2119.77   232.7 2097.77     236 2094.76   239.3 2090.18   242.5 2083.84
   245.8 2078.69   249.1 2074.76  258.362069.938   291.7 2068.98   304.62067.453
   314.6 2065.94     3282067.406   353.9 2070.36   376.8 2071.59  439.892077.633
   549.8 2083.96   585.6 2088.63   686.2 2094.88   728.4 2099.43   757.7 2104.13
#Mann= 5 ,-1 , 0
       0     .12       0  258.36    .016       0   304.6    .045       0
     328    .016       0  439.89     .12       0
Bank Sta=304.6,328
XS Rating Curve= 0 ,0
Exp/Cntr=0.3,0.1

Type RM Length L Ch R = 1 ,1358.3  ,247.2,250,248.8
XS GIS Cut Line= 3
     2157761.107      193115.361     2158059.781      193093.975
     2158423.562      193093.975
#Sta/Elev= 30
       0 2085.95    32.6 2085.69   60.84 2083.69    74.9 2082.45    97.6 2078.41
   130.2 2073.63   149.7 2066.38  158.882063.566     166 2062.18   185.5 2060.72
  200.752060.736     205 2061.02   211.6 2059.78   234.3 2061.04  242.782059.104
   250.6 2058.45   266.9 2059.42   276.7 2058.63   286.4 2058.72   299.4 2056.95
   302.7 2057.53  304.152058.765   309.3 2063.93   312.6 2066.51   315.8 2067.99
   322.4 2069.34   397.8 2076.04   496.1 2087.13   594.4  2101.6   663.2 2113.81
#Mann= 7 ,-1 , 0
       0     .12       0   60.84     .06       0  158.88     .12       0
  200.75    .016       0  242.78     .12       0   286.4    .045       0
  304.15     .12       0
#XS Ineff= 2 , 0
          233.25 2062.55
Permanent Ineff=
       F       F
Bank Sta=286.4,304.15
XS Rating Curve= 0 ,0
Exp/Cntr=0.3,0.1

Type RM Length L Ch R = 1 ,1108.3  ,250.2,250,251.4
XS GIS Cut Line= 3
     2157709.019      193324.083      2158078.41      193342.186
     2158440.951      193324.359
#Sta/Elev= 30
       0 2078.27   30.022078.008    85.1 2079.33   127.6 2078.84   140.7 2077.23
   166.9 2071.94   186.6 2068.69   222.6 2066.06   229.1 2064.19   245.5  2057.8
   255.3 2056.14   291.3 2055.17  311.162055.365   327.3 2055.61   330.6 2055.32
   337.1 2053.58  341.732053.666  357.142053.705     360 2053.48   366.6 2052.16
   373.1 2051.95   379.6 2052.33  382.422053.484   392.7 2060.46   402.5 2063.99
   458.1 2077.38   546.4 2093.77   582.4 2101.35   703.4 2124.83   732.8 2128.88
#Mann= 7 ,-1 , 0
       0     .12       0   30.02     .06       0  311.16     .12       0
  341.73    .016       0  357.14     .12       0     360    .045       0
  382.42     .12       0
Bank Sta=360,382.42
XS Rating Curve= 0 ,0
Exp/Cntr=0.3,0.1

Type RM Length L Ch R = 1 ,858.3   ,291.9,306.4,320
XS GIS Cut Line= 3
     2157698.931      193581.503     2158062.834       193589.41
     2158426.678       193601.06
#Sta/Elev= 30
       0 2072.72   40.782068.222    75.4 2065.12   111.5  2064.8  143.662062.873
     164  2061.8   193.5 2059.05     200 2057.34  216.032049.846   219.7 2048.69
   226.3 2048.11   249.2  2049.9  313.85 2050.59   327.9 2050.42   337.8  2048.8
   354.2 2049.03   360.7 2046.53     364 2045.99   370.6 2046.27   376.12048.893
   396.8 2062.81   442.7 2085.68   455.8  2091.5   465.7 2094.44     482 2097.36
   518.1 2102.16   550.9 2107.98   596.8 2114.15   642.8 2118.46     728 2122.91
#Mann= 7 ,-1 , 0
       0     .12       0   40.78     .06       0  143.66     .12       0
  216.03     .06       0  313.85    .016       0   354.2    .045       0
   376.1     .12       0
#XS Ineff= 2 , 0
           297.4 2051.75
Permanent Ineff=
       F       F
Bank Sta=354.2,376.1
XS Rating Curve= 0 ,0
Exp/Cntr=0.3,0.1

Type RM Length L Ch R = 1 ,551.9   ,387.2,377.4,367.4
XS GIS Cut Line= 3
     2157693.398       193651.82     2158097.912      193955.639
     2158419.093      193696.959
#Sta/Elev= 30
       0 2068.07    32.6 2064.24    61.32062.037    84.9 2060.84   176.2 2058.94
   195.8 2057.93   231.7 2052.97   264.4 2050.25   293.8 2045.46  310.242044.245
   326.4 2043.23   352.5 2043.22  357.85 2041.98   362.3 2040.06   368.8 2039.51
   381.9 2041.95   391.7 2043.78   417.8 2058.06   434.1 2062.94   453.7 2063.78
   505.9 2062.41  536.612065.775   561.5 2067.84   617.2 2076.64  663.44 2081.92
  708.912085.356  824.712090.468  875.992093.597  884.07 2094.31   918.3 2097.14
#Mann= 11 ,-1 , 0
       0     .12       0    61.3     .06       0  310.24    .016       0
  357.85    .045       0   381.9     .12       0  536.61     .06       0
  663.44     .12       0  708.91     .06       0  824.71     .12       0
  875.99     .08       0  884.07     .12       0
Bank Sta=357.85,381.9
XS Rating Curve= 0 ,0
Exp/Cntr=0.3,0.1

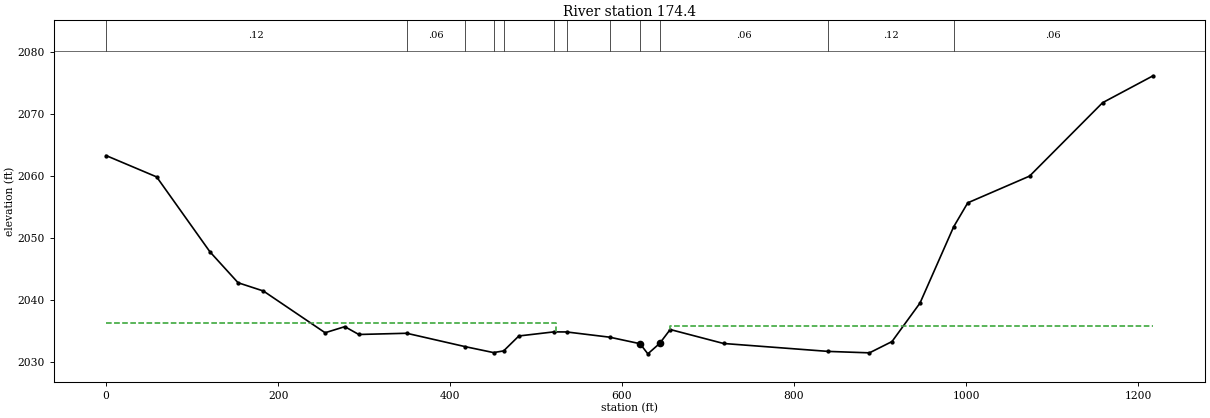
Type RM Length L Ch R = 1 ,174.4   ,173.1,174.4,175.7
XS GIS Cut Line= 4
     2157689.926      193740.361      2157750.69      194193.486
     2158028.468      194250.778     2158351.384      193900.084
#Sta/Elev= 30
       0 2063.23    58.8 2059.79   120.8 2047.71   153.5 2042.73   182.9  2041.4
   254.7 2034.67   277.6 2035.65   293.9 2034.39   349.62034.586  417.832032.422
  450.542031.472   462.32031.743     480 2034.15  520.75 2034.81  535.482034.798
  585.582033.955  620.892032.904     630 2031.27   643.72032.942     656 2035.19
     718 2032.94  839.842031.661   887.7 2031.43   913.9 2033.25   946.5 2039.46
  985.572051.734    1002 2055.61  1073.9 2059.92  1158.8 2071.75  1217.5 2076.09
#Mann= 12 ,-1 , 0
       0     .12       0   349.6     .06       0  417.83     .12       0
  450.54     .06       0   462.3     .12       0  520.75     .06       0
  535.48    .016       0  585.58     .12       0  620.89    .045       0
   643.7     .06       0  839.84     .12       0  985.57     .06       0
#XS Ineff= 2 , 0
          523.76 2036.23  656.19         2035.82
Permanent Ineff=
       F       F
Bank Sta=620.89,643.7
XS Rating Curve= 0 ,0
Exp/Cntr=0.3,0.1

Chan Stop Cuts=-1
Use User Specified Reach Order=0
Composite Channel Slope=5